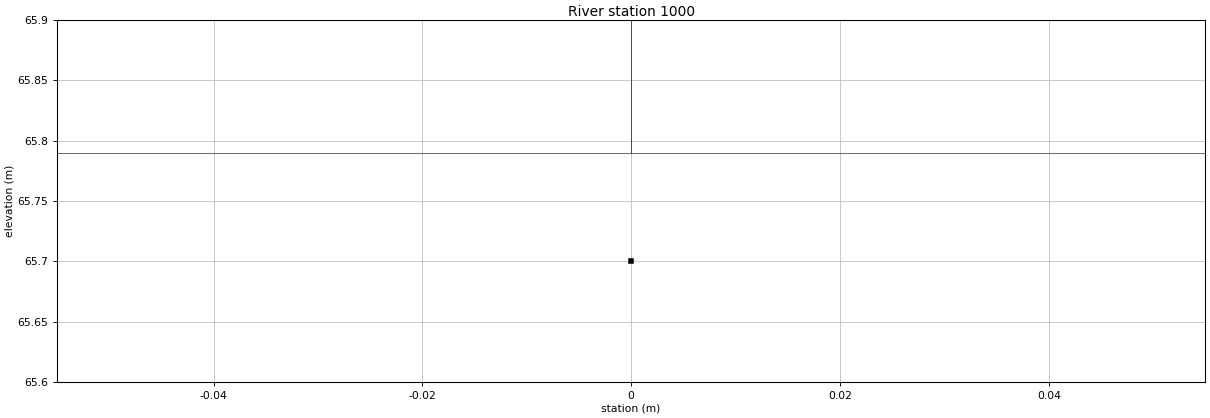
--- HECRAS_v0_EstructuraCanalPpalContraccion.prj (project) ---

Proj Title=HECRAS_v0_EstructuraCanalPpalContraccion
Current Geom=g01
Default Exp/Contr=0.3,0.1
SI Units
Geom File=g01
Y Axis Title=Elevation
X Axis Title(PF)=Main Channel Distance
X Axis Title(XS)=Station
BEGIN DESCRIPTION:
END DESCRIPTION:
DSS Export Rating Curves= 0
DSS Export Rating Curve Sorted= 0
DSS Export Volume Flow Curves= 0
DXF OffsetX= 0
DXF OffsetY= 0
DXF ScaleX= 1
DXF ScaleY= 10

--- HECRAS_v0_EstructuraCanalPpalContraccion.g01 (geometry) ---

Geom Title=HECRAS_v0_EstructuraCanalPpalContraccion
Program Version=6.70

River Reach=CanalPrincipal  ,CanalPrincipal
Reach XY= 2
        1001000.        1000000.        1000000.        1000000.

Type RM Length L Ch R = 1 ,1000    ,1000,1000,1000
#Sta/Elev= 1
       0    65.7
#Mann= 3 ,0,0
       0    .035       0             .02       0            .035       0
XS Rating Curve= 0 ,0
Exp/Cntr=0.3,0.1
LCMann Table=0

Chan Stop Cuts=-1
Use User Specified Reach Order=0
Composite Channel Slope=5